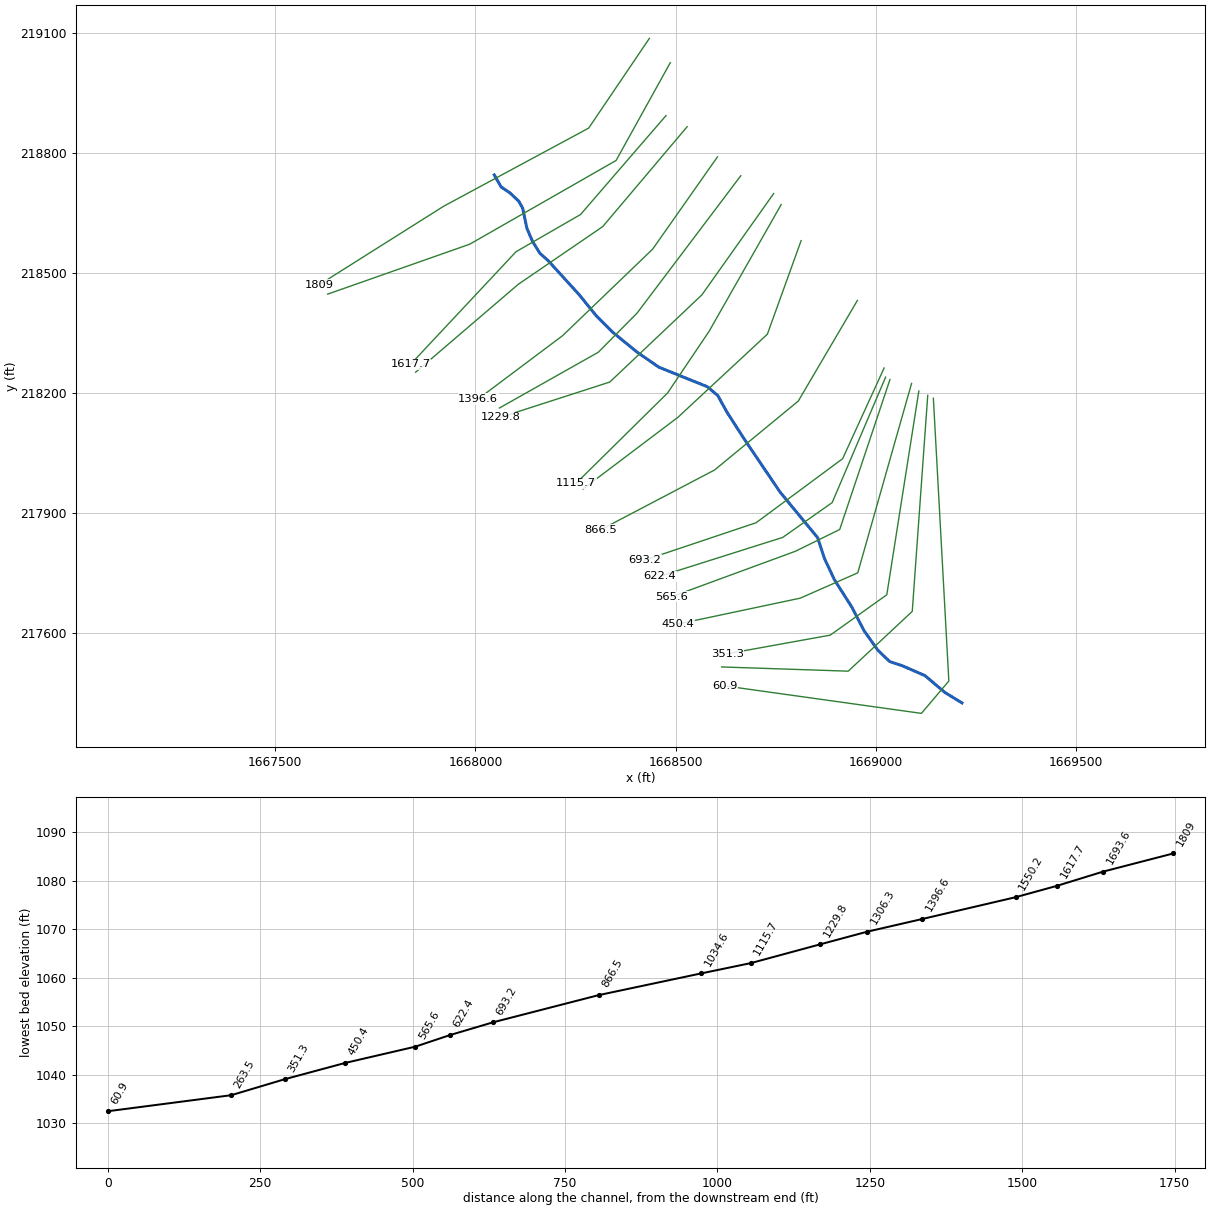
--- np3.prj (project) ---

Proj Title=np3
Current Plan=p01
Default Exp/Contr=0,0
English Units
Geom File=g01
Flow File=f01
Plan File=p01
BEGIN DESCRIPTION:
END DESCRIPTION:
DSS Export Rating Curves= 0
DSS Export Rating Curve Sorted= 0
DSS Export Volume Flow Curves= 0
DXF OffsetX= 0
DXF OffsetY= 0
DXF ScaleX= 0
DXF ScaleY= 0

--- np3.p01 (plan) ---

Plan Title=Floodplain
Program Version=4.00
Geom File=g01
Flow File=f01
K Sum by GR=0
Std Step Tol=0.01
Critical Tol=0.01
Num of Std Step Trials=20
Max Error Tol=0.3
Flow Tol Ratio=0.001
Split Flow NTrial=30
Split Flow Tol=0.02
Split Flow Ratio=0.02
Log Output Level=0
Friction Slope Method=1
Unsteady Friction Slope Method=2
Unsteady Bridges Friction Slope Method=1
Global Log Level=0
CheckData=False
Run HTab=0
Run UNet=0
Run PostProcess=0
UNET Theta=0
UNET Theta Warmup=0
UNET ZTol=0
UNET ZSATol=0
UNET MxIter=0
UNET MaxInSteps=0
UNET DtIC=0
UNET DtMin=0
UNET MaxCRTS=0
UNET WFStab=0
UNET SFStab=0
UNET WFX=0
UNET SFX=0
UNET DSS MLevel=0
UNET DZMax Abort=0
UNET Convert EG Bridges=0
UNET Use Existing IB Tables=0
UNET Froude Limit=0
UNET Froude Power=0
Write IC File=0
Echo Input=False
Echo Output=False
Write Detailed=0

--- np3.f01 (steady flow) ---

Flow Title=NFF Regression Equation
Program Version=4.00
Number of Profiles=1
Profile Names=P100yr
River Rch & RM=np3,Main      ,1809
     363
River Rch & RM=np3,Main      ,263.5
     381
Boundary for River Rch & Prof#=np3,Main      ,1
Up Type=0
Dn Type=3
Dn Slope=0.029263

--- np3.g01 (geometry) ---

Geom Title=USGS 10m DEM
Program Version=4.00

River Reach=np3             ,Main
Reach XY= 30
     1668047.041      218744.976     1668064.033      218715.258
     1668086.831      218699.688     1668108.517      218679.114
      1668117.97      218661.876     1668128.535      218611.831
     1668142.576      218579.003     1668160.787      218549.553
     1668181.917      218530.647     1668258.557      218446.506
     1668301.657      218393.397     1668342.885      218352.157
     1668404.103      218302.168     1668458.451      218264.675
     1668579.497       218215.92     1668605.631      218193.677
     1668627.742      218153.445     1668671.464      218085.341
     1668761.409      217952.256     1668855.105      217838.537
     1668871.966      217786.681     1668896.948      217733.573
      1668940.67      217664.844      1668970.65      217606.738
     1669005.628      217557.378     1669034.988      217529.259
     1669065.599      217519.259     1669123.072      217494.261
     1669172.422      217452.395     1669215.437      217426.077

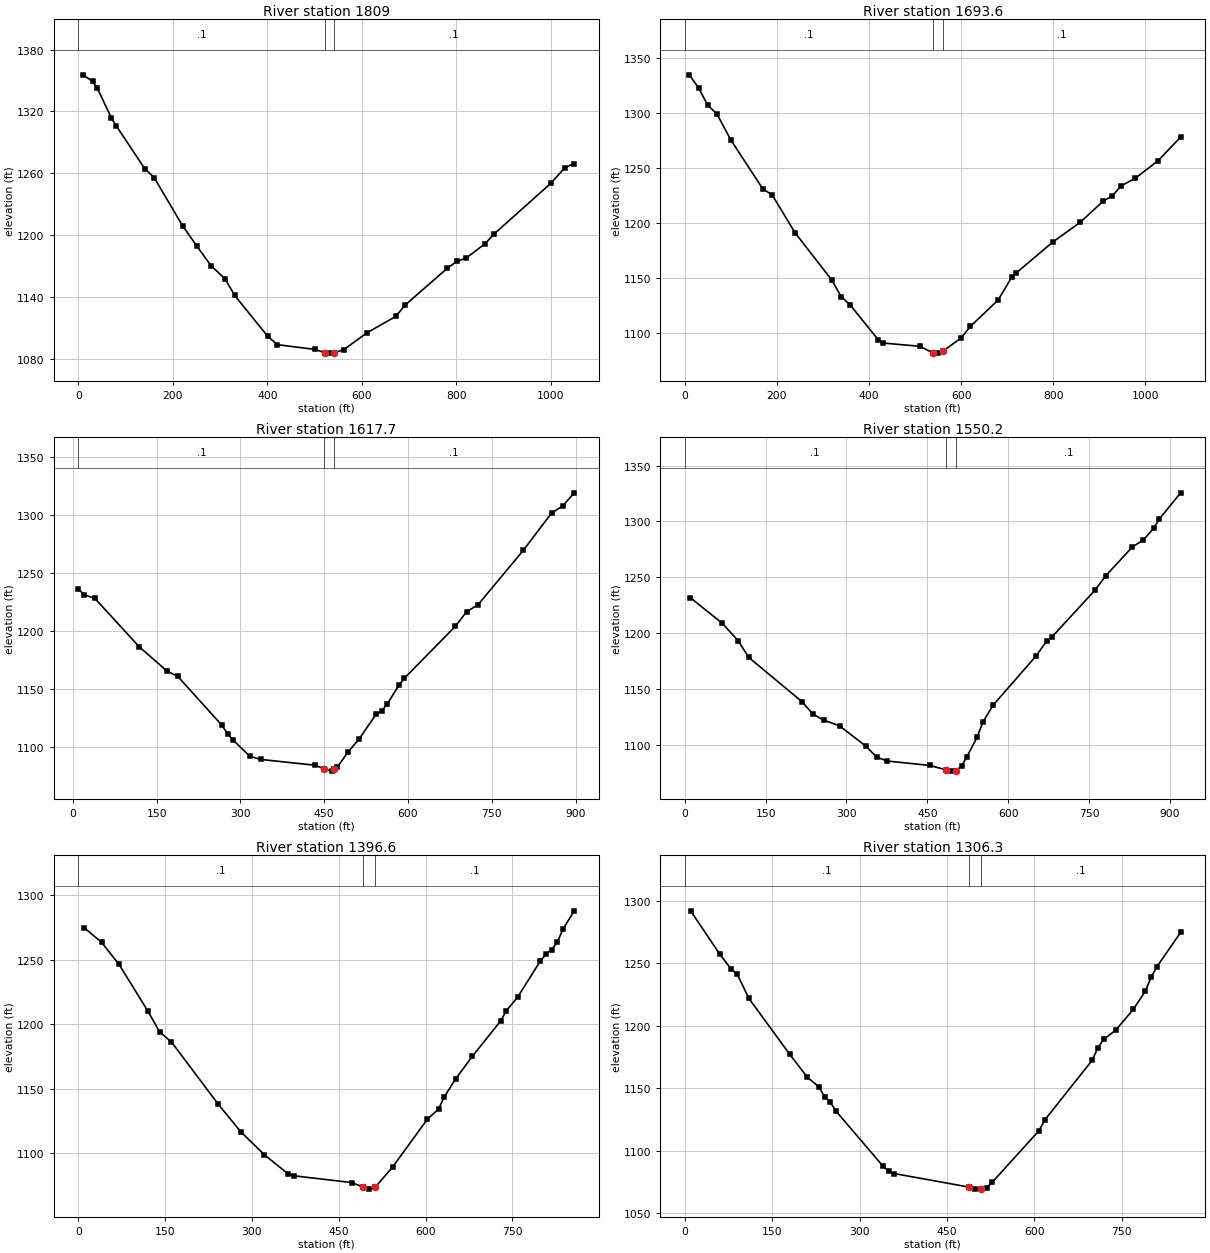
Type RM Length L Ch R = 1 ,1809    ,114.5,115.4,116.3
XS GIS Cut Line= 4
     1668434.607      219086.334     1668282.884      218862.068
     1667920.857      218666.996     1667609.795      218470.849
#Sta/Elev= 30
      10 1355.48    30.1 1349.07    40.1 1342.61    70.2 1313.46    80.2 1306.12
   140.4 1264.61   160.5 1255.86   220.6 1209.21   250.7  1189.5   280.8 1170.55
   310.9 1157.49   330.9 1141.56   401.2 1101.86   421.2 1093.88   501.5 1089.17
   521.6 1086.09   531.6 1085.64   541.6 1086.13   561.6 1088.93   611.8 1105.52
     672 1121.23   691.9 1132.25   781.4 1168.05   801.3 1174.63   821.2 1177.84
   860.9 1191.69   880.8 1201.41  1000.1 1250.21  1029.9 1265.39  1049.7 1269.47
#Mann= 3 , 0 , 0
       0      .1       0   521.6    .045       0   541.6      .1       0
Bank Sta=521.6,541.6
XS Rating Curve= 0 ,0
Exp/Cntr=0.3,0.1

Type RM Length L Ch R = 1 ,1693.6  ,75.9,75.9,75.9
XS GIS Cut Line= 4
     1668486.743      219025.508     1668351.423      218781.228
     1667985.881      218572.096     1667630.884      218447.319
#Sta/Elev= 30
      10 1334.79    29.9 1322.86    49.9 1307.19    69.8 1299.18    99.7 1275.78
   169.5 1231.07   189.5 1225.78   239.4 1191.29   319.4 1148.14   339.4 1133.32
   359.5  1125.5   419.6 1094.24   429.7 1091.08   509.9 1088.11     540 1081.98
     550 1081.88     560 1083.51   600.1 1095.68   620.2 1106.16   680.3 1130.11
   710.3 1151.13   720.2 1154.96   799.4 1182.91   858.8 1200.82   908.3 1219.91
   928.1 1224.72     948 1234.07   977.7 1240.65  1027.2 1256.54  1076.7 1278.17
#Mann= 3 , 0 , 0
       0      .1       0     540    .045       0     560      .1       0
Bank Sta=540,560
XS Rating Curve= 0 ,0
Exp/Cntr=0.3,0.1

Type RM Length L Ch R = 1 ,1617.7  ,65.7,67.6,69.5
XS GIS Cut Line= 4
      1668476.05      218893.288     1668262.524      218646.152
     1668101.392      218553.229     1667838.439      218272.483
#Sta/Elev= 30
     9.9 1236.04    19.8 1231.02    39.6 1227.74   118.8  1186.1   168.2 1165.32
     188 1160.49   267.2 1118.29   277.1 1110.96     287 1105.65   316.7 1091.83
   336.4 1089.01   434.3 1083.98  450.03 1080.75   463.7 1078.94  467.92 1080.43
   473.4 1082.38     493 1095.72   512.6 1106.68     543 1128.14   553.1 1130.93
   563.2 1137.06   583.5 1152.86   593.6 1159.07   684.7 1203.75   704.9 1216.31
   725.2 1222.32   806.2 1269.12   856.8 1301.27     877 1307.52   897.3 1318.75
#Mann= 3 , 0 , 0
     9.9      .1       0  450.03    .045       0  467.92      .1       0
Bank Sta=450.03,467.92
XS Rating Curve= 0 ,0
Exp/Cntr=0.3,0.1

Type RM Length L Ch R = 1 ,1550.2  ,149.4,153.6,157.8
XS GIS Cut Line= 4
     1668528.921      218865.583     1668318.032      218616.031
     1668107.143      218471.923     1667850.561      218252.247
#Sta/Elev= 30
     9.9 1231.95    69.3    1209      99 1193.34   118.8 1178.29   217.8 1138.59
   237.6 1127.69   257.4 1122.29   287.1 1117.14   336.6 1098.74   356.2 1088.96
   375.8 1085.64   454.4 1081.69   483.7 1077.86   493.7  1076.6   503.7 1077.12
   513.4 1081.13   523.2 1089.35   542.9 1107.48   552.7 1120.24   572.3 1135.79
   651.7 1179.67   671.6 1193.21   681.5 1196.87     761  1238.5   780.8 1251.31
   830.5 1277.28   850.4 1283.32   870.3 1294.15   880.2  1302.1   919.9 1325.66
#Mann= 3 , 0 , 0
       0      .1       0   483.7    .045       0   503.7      .1       0
Bank Sta=483.7,503.7
XS Rating Curve= 0 ,0
Exp/Cntr=0.3,0.1

Type RM Length L Ch R = 1 ,1396.6  ,89.7,90.3,90.9
XS GIS Cut Line= 4
      1668604.49      218790.015     1668442.808      218559.794
      1668217.86      218343.632      1668006.97      218185.465
#Sta/Elev= 30
      10 1274.91    40.2  1263.5    70.3 1246.42   120.6 1209.87   140.7 1193.85
   160.8 1186.33   241.1 1138.32   281.3 1116.29   321.6 1098.75   361.8 1084.15
   371.9 1082.47   472.5 1077.17   492.7 1073.61   502.7 1072.09   512.7 1073.38
     543 1089.15   603.1 1126.25   622.6 1134.24   632.4 1143.61   651.9 1157.52
   681.2 1175.22     730 1202.61   739.7  1210.4   759.3 1221.07   798.3 1248.88
   808.1 1254.42   817.9 1257.83   827.6 1263.51   837.4 1273.53   856.9 1287.95
#Mann= 3 , 0 , 0
       0      .1       0   492.7    .045       0   512.7      .1       0
Bank Sta=492.7,512.7
XS Rating Curve= 0 ,0
Exp/Cntr=0.3,0.1

Type RM Length L Ch R = 1 ,1306.3  ,77.4,76.5,75.6
XS GIS Cut Line= 4
     1668662.885       218743.03     1668403.886      218400.005
     1668307.009      218302.139     1668059.873      218162.754
#Sta/Elev= 30
      10 1292.13      60 1257.52      80 1245.26      90 1241.47     110  1222.1
   179.9 1177.49   209.9 1159.27   229.9 1151.38   239.9 1143.52   249.9 1138.88
   259.9 1131.73   339.9 1088.06   349.9 1083.82   359.9  1081.9   488.7 1071.05
   498.7 1069.47   508.7 1069.67   518.3 1070.63   528.2 1075.18   608.1 1116.23
   618.2  1124.9   699.3 1172.47   709.4 1182.73   719.5  1189.4   739.8 1196.63
   770.2 1213.38   790.5 1227.67   800.6 1238.84   810.7 1247.54   851.3  1274.8
#Mann= 3 , 0 , 0
       0      .1       0   488.7    .045       0   508.7      .1       0
Bank Sta=488.7,508.7
XS Rating Curve= 0 ,0
Exp/Cntr=0.3,0.1

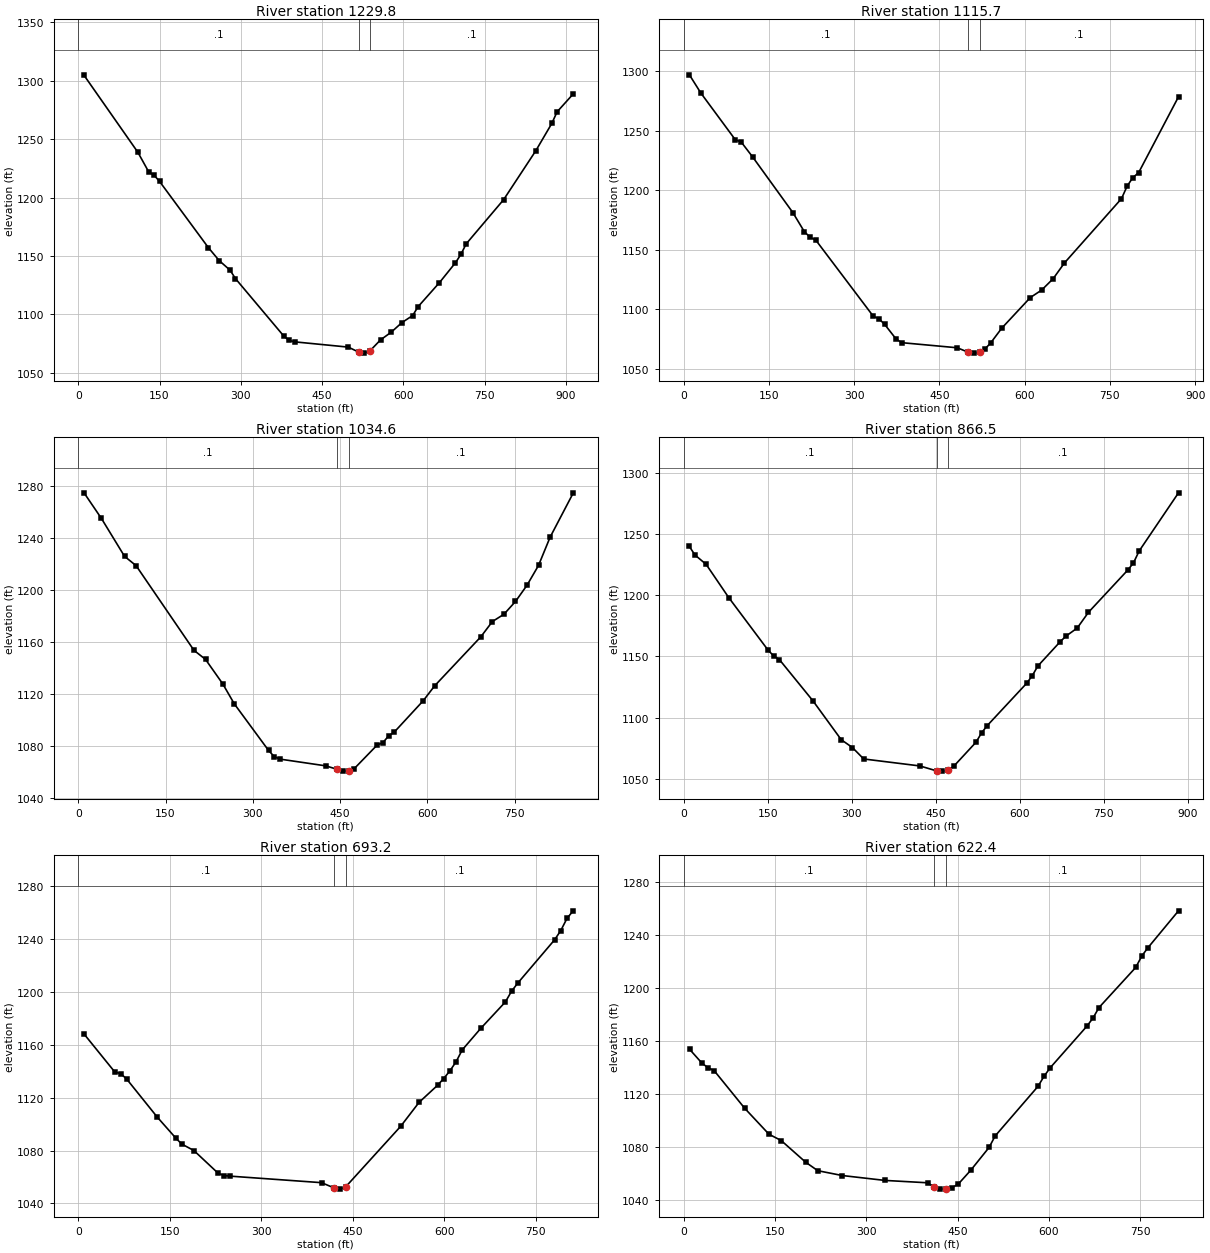
Type RM Length L Ch R = 1 ,1229.8  ,108.5,114,119.5
XS GIS Cut Line= 4
     1668745.083      218698.629     1668565.827      218445.562
     1668335.606      218227.643     1668063.207      218139.772
#Sta/Elev= 30
      10 1305.16     110 1238.83   130.1 1221.95   140.1 1219.12   150.1 1213.85
   240.1  1157.2   260.1 1146.09   280.1 1137.92   290.1 1130.68   379.5 1081.37
   389.4 1077.75   399.3 1076.54   498.3 1072.03   518.1 1067.65   528.1 1066.88
   538.1 1068.71   557.8  1078.2   577.6 1084.81   597.4 1093.06   617.2 1099.08
   627.1 1106.62   666.6 1127.25   696.2  1144.3   706.1 1151.37     716 1160.48
     785 1198.25   844.3 1240.07   873.9  1263.5   883.7 1273.47   913.3  1288.7
#Mann= 3 , 0 , 0
       0      .1       0   518.1    .045       0   538.1      .1       0
Bank Sta=518.1,538.1
XS Rating Curve= 0 ,0
Exp/Cntr=0.3,0.1

Type RM Length L Ch R = 1 ,1115.7  ,86.9,81.2,75.4
XS GIS Cut Line= 4
     1668763.716      218670.866     1668583.801      218354.532
     1668480.004      218200.319      1668251.65      217974.931
#Sta/Elev= 30
    10.1 1297.13    30.3 1281.78      91 1242.44   101.1 1240.69   121.3  1228.1
   192.1 1181.26   212.3 1165.23   222.4 1160.49   232.5 1158.08   333.6 1094.07
   343.7 1091.86   353.8  1087.1   373.7 1074.91   383.5 1071.81   481.3 1067.51
   500.7 1063.78   510.7    1063   520.7 1063.78   530.2 1066.52     540 1071.45
   559.8 1084.05     610 1109.77     630 1116.09   650.1 1125.59   670.1 1138.92
   770.4 1192.98   780.4 1203.57   790.4 1210.69   800.5 1214.79   870.7 1278.66
#Mann= 3 , 0 , 0
       0      .1       0   500.7    .045       0   520.7      .1       0
Bank Sta=500.7,520.7
XS Rating Curve= 0 ,0
Exp/Cntr=0.3,0.1

Type RM Length L Ch R = 1 ,1034.6  ,169.6,168.1,166.6
XS GIS Cut Line= 4
     1668813.622      218580.883     1668729.266      218347.147
     1668506.075      218139.772     1668268.824      217960.516
#Sta/Elev= 30
     9.9 1274.69    39.8 1254.98    79.5 1225.91    99.4 1218.72   198.8  1153.7
   218.7 1146.72   248.5 1127.79   268.1  1112.6   327.1 1076.73   336.9 1071.99
   346.8  1070.1   425.4 1064.93   444.9 1062.28   454.9 1060.88   464.9 1060.99
   474.5 1062.88   513.8 1080.99   523.7 1082.81   533.5 1088.02   543.3 1090.97
   592.8 1114.93   612.6 1126.46   691.9 1164.09   711.7 1175.79   731.6 1181.41
   751.4  1191.2   771.2 1203.66     791 1218.88   810.9 1240.57   850.5 1274.39
#Mann= 3 , 0 , 0
       0      .1       0   444.9    .045       0   464.9      .1       0
Bank Sta=444.9,464.9
XS Rating Curve= 0 ,0
Exp/Cntr=0.3,0.1

Type RM Length L Ch R = 1 ,866.5   ,174.6,173.3,172
XS GIS Cut Line= 4
     1668954.215      218431.503     1668806.592      218180.193
      1668597.46      218007.967      1668312.76      217858.587
#Sta/Elev= 30
    10.1  1239.9    20.1 1232.92    40.2 1225.21    80.4 1198.17   150.8 1155.18
   160.8 1150.47   170.9 1147.52   231.2 1113.64   281.4 1082.09   301.5 1075.63
   321.6 1066.33   421.9 1060.64     452 1056.58     462  1056.4     472 1056.98
   482.1  1060.2   522.2 1080.01   532.3 1087.74   542.3 1093.59   612.6 1128.09
   622.7 1134.35   632.7 1142.24   672.9 1162.24   682.9 1166.63     703 1173.24
   723.1  1186.1   793.5 1220.67   803.5 1226.47   813.6 1236.13   883.9 1283.64
#Mann= 3 , 0 , 0
       0      .1       0     452    .045       0     472      .1       0
Bank Sta=452,472
XS Rating Curve= 0 ,0
Exp/Cntr=0.3,0.1

Type RM Length L Ch R = 1 ,693.2   ,71.4,70.8,70.2
XS GIS Cut Line= 4
     1669020.997      218262.791     1668917.309      218036.085
     1668701.148      217876.161     1668423.477      217783.018
#Sta/Elev= 30
      10 1167.92    59.8  1139.5    69.8 1138.22    79.8 1133.86   129.6 1105.23
   159.5 1089.61   169.5 1084.94   189.5    1080   229.3 1062.79   239.3 1061.04
   249.3 1060.61   398.7 1055.68   418.6 1051.84   428.6 1050.79   438.6 1052.67
   528.3 1098.27   558.6 1116.49   588.9 1129.41     599 1134.54   609.1 1140.32
   619.2 1147.17   629.3 1156.18   659.6 1172.45     700 1192.48   710.1 1200.55
   720.2  1206.7   780.8  1239.6   790.9  1246.6     801 1255.71   811.1  1261.5
#Mann= 3 , 0 , 0
       0      .1       0   418.6    .045       0   438.6      .1       0
Bank Sta=418.6,438.6
XS Rating Curve= 0 ,0
Exp/Cntr=0.3,0.1

Type RM Length L Ch R = 1 ,622.4   ,60.8,56.8,52.9
XS GIS Cut Line= 4
     1669024.692      218239.861     1668891.238      217926.492
      1668767.67      217839.501     1668461.222      217742.623
#Sta/Elev= 30
      10 1153.74    30.1 1143.39    40.1 1139.89    50.1 1137.74   100.2 1109.32
   140.2 1089.65   160.3 1084.88   200.4 1068.53   220.4 1062.08   260.5 1058.44
   330.6 1054.74     401 1052.94   411.2  1049.7   421.2 1048.15   431.2 1048.24
   441.3 1049.32   451.4 1052.06   471.6 1062.36   501.8 1079.64   511.8 1088.33
   582.1 1125.77   592.2  1133.5   602.2 1139.87   662.5 1171.31   672.5 1177.44
   682.5 1185.46   742.8 1215.76   752.9 1224.47   762.9 1230.68   813.1 1258.57
#Mann= 3 , 0 , 0
       0      .1       0   411.2    .045       0   431.2      .1       0
Bank Sta=411.2,431.2
XS Rating Curve= 0 ,0
Exp/Cntr=0.3,0.1

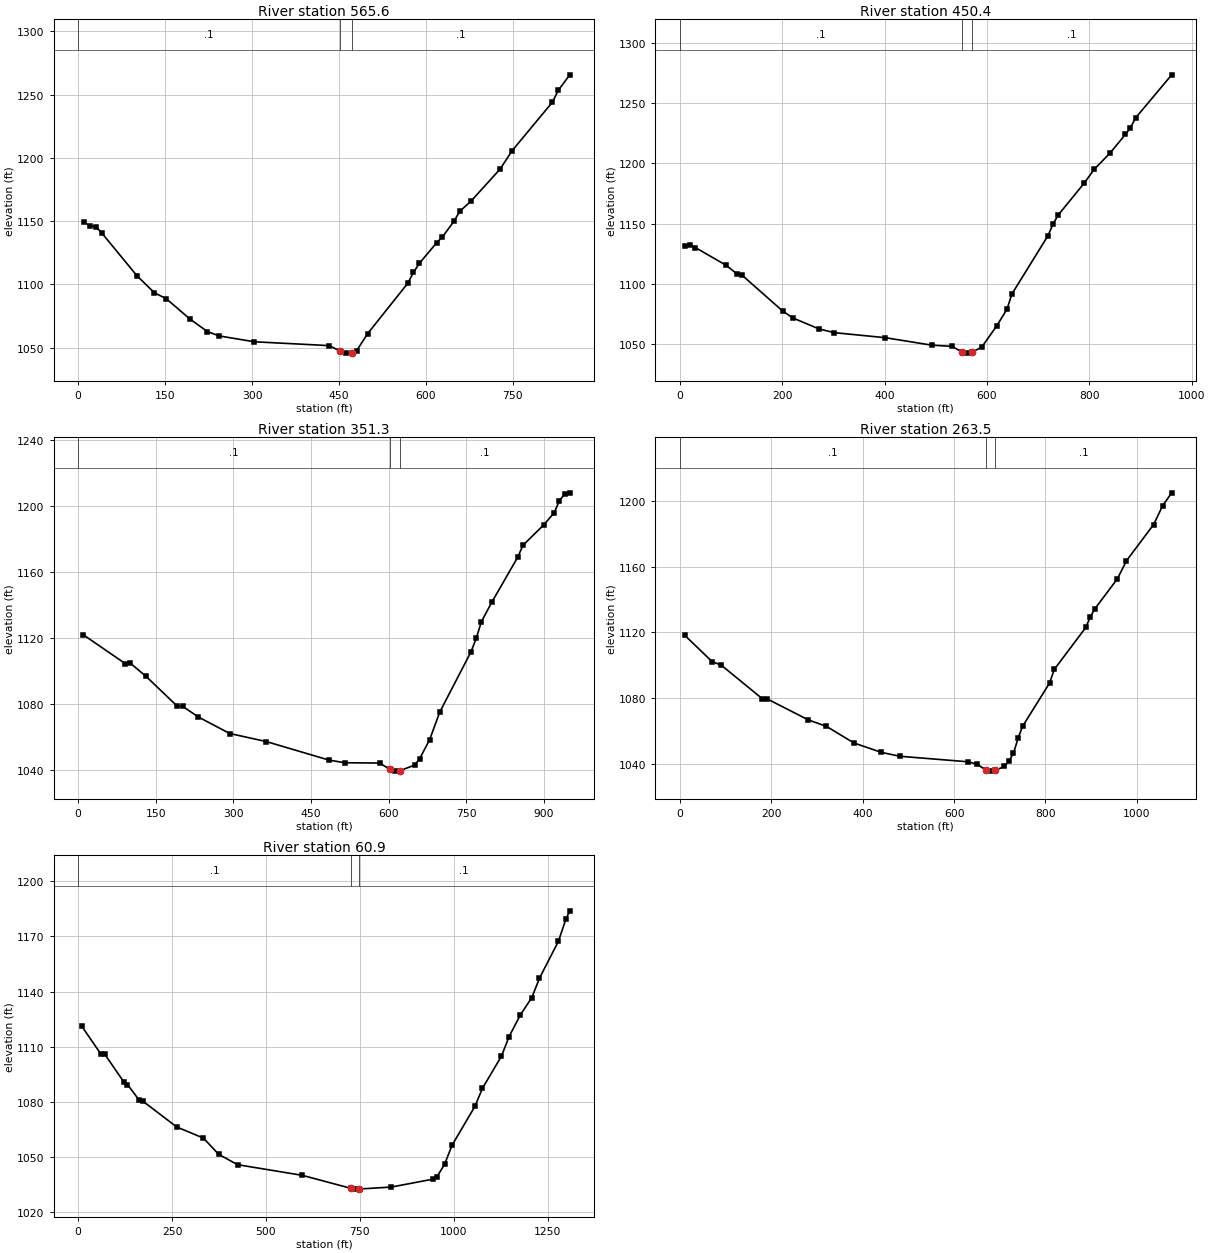
Type RM Length L Ch R = 1 ,565.6   ,116.2,115.1,114.1
XS GIS Cut Line= 4
     1669035.566       218233.93     1668910.021      217859.271
     1668799.304      217804.901     1668489.889      217691.219
#Sta/Elev= 30
    10.1 1149.35    20.3 1146.38    30.4 1145.67    40.5 1140.82   101.3 1106.97
   131.7 1093.35     152 1088.78   192.5  1072.8   222.9 1062.83   243.2 1059.35
   303.9 1054.73   433.1 1051.69   451.6 1047.44   461.6 1045.76   471.6 1046.04
   480.5 1047.72   499.5 1061.24   568.4 1100.82   578.4 1109.46   588.4 1116.57
   618.4 1132.93   628.4 1137.52   648.3 1149.94   658.3 1157.75   678.3 1166.11
   728.2  1191.3   748.2 1205.42   818.2 1244.04   828.1 1253.25   848.1 1265.57
#Mann= 3 , 0 , 0
       0      .1       0   451.6    .045       0   471.6      .1       0
Bank Sta=451.6,471.6
XS Rating Curve= 0 ,0
Exp/Cntr=0.3,0.1

Type RM Length L Ch R = 1 ,450.4   ,94,99.2,104.3
XS GIS Cut Line= 4
     1669089.536      218224.128     1668955.164      217751.026
     1668811.496      217687.759     1668506.075      217623.093
#Sta/Elev= 30
      10 1131.53    20.1 1132.25    30.1 1130.11    90.3 1115.35   110.4 1108.55
   120.4 1107.49   200.7 1077.34   220.8  1071.6     271  1062.6   301.1 1059.43
   401.5 1055.21   491.8 1049.03   531.1    1048   550.5  1043.6   560.5  1042.4
   570.5 1043.05   589.9  1047.5   619.4 1065.32     639 1078.88   648.8 1091.63
   719.3  1140.1   729.4 1150.01   739.4 1157.29   789.8 1183.61   809.9 1195.35
   840.1 1208.47   870.4 1224.12   880.4 1229.74   890.5 1237.95     961 1273.69
#Mann= 3 , 0 , 0
       0      .1       0   550.5    .045       0   570.5      .1       0
Bank Sta=550.5,570.5
XS Rating Curve= 0 ,0
Exp/Cntr=0.3,0.1

Type RM Length L Ch R = 1 ,351.3   ,84.5,87.8,91.1
XS GIS Cut Line= 4
     1669107.729      218205.262     1669027.657      217696.162
     1668886.295       217595.33     1668629.274      217548.869
#Sta/Elev= 30
    10.1 1121.64    90.9 1104.23   101.1 1104.39   131.4 1096.42     192 1078.26
   202.1 1078.27   232.4 1071.84     293 1061.84   363.8 1056.94     485 1045.71
   515.4 1044.12   582.9 1043.94   601.8 1040.21   611.8 1039.04   621.8 1039.28
   650.4 1042.72   660.1 1046.57   679.4 1058.17     699 1074.91   759.3 1111.38
   769.4 1119.56   779.4 1129.65   799.5 1141.42   849.7 1168.76   859.8 1175.95
     900 1188.31     920 1195.61   930.1 1202.93   940.1  1206.9   950.2 1207.69
#Mann= 3 , 0 , 0
       0      .1       0   601.8    .045       0   621.8      .1       0
Bank Sta=601.8,621.8
XS Rating Curve= 0 ,0
Exp/Cntr=0.3,0.1

Type RM Length L Ch R = 1 ,263.5   ,199.5,202.5,205.6
XS GIS Cut Line= 4
     1669129.956      218194.252     1669091.293      217654.727
     1668931.369      217505.347     1668615.034      217515.891
#Sta/Elev= 30
      10 1118.32    70.1 1102.28    90.2 1100.11   180.3 1079.68   190.3 1079.68
   280.5  1066.9   320.5 1062.93   380.6 1052.85   440.7 1047.13   480.8 1044.78
   630.4 1041.41   650.3 1039.97   670.2 1036.22   680.2 1035.74   690.2 1036.19
     710  1038.6     720 1041.99   729.9 1046.55   739.9 1055.67   749.8 1062.93
   809.2 1089.36   819.1 1097.47   888.3 1123.01   898.2 1129.56   908.1 1134.31
   957.6 1152.64   977.3 1163.54  1036.7  1185.5  1056.5 1196.97  1076.3 1204.77
#Mann= 3 , 0 , 0
       0      .1       0   670.2    .045       0   690.2      .1       0
Bank Sta=670.2,690.2
XS Rating Curve= 0 ,0
Exp/Cntr=0.3,0.1

Type RM Length L Ch R = 1 ,60.9    ,57.1,60.9,64.8
XS GIS Cut Line= 4
     1669144.016      218187.222     1669182.678      217480.743
     1669114.139      217399.902     1668623.822      217468.441
#Sta/Elev= 30
    10.1 1120.98    60.6 1105.99    70.8 1105.93   121.3 1090.88   131.4 1089.38
   161.7 1081.07   171.8 1080.39   262.8 1066.23   333.6 1060.21     374 1051.38
   424.5 1045.73   596.4 1039.95   726.4 1032.85   736.4 1032.43   746.4 1032.47
   833.7 1033.56   944.9 1037.88     955  1039.2   975.2 1045.89   995.4 1056.42
    1056 1077.45  1076.2 1087.37  1126.7 1104.83  1146.9 1115.46  1177.3  1127.4
  1207.6 1136.75  1227.8 1147.24  1278.3 1167.39  1298.5 1179.61  1308.6 1183.96
#Mann= 3 , 0 , 0
       0      .1       0   726.4    .045       0   746.4      .1       0
Bank Sta=726.4,746.4
XS Rating Curve= 0 ,0
Exp/Cntr=0.3,0.1

Chan Stop Cuts=-1
Use User Specified Reach Order=0